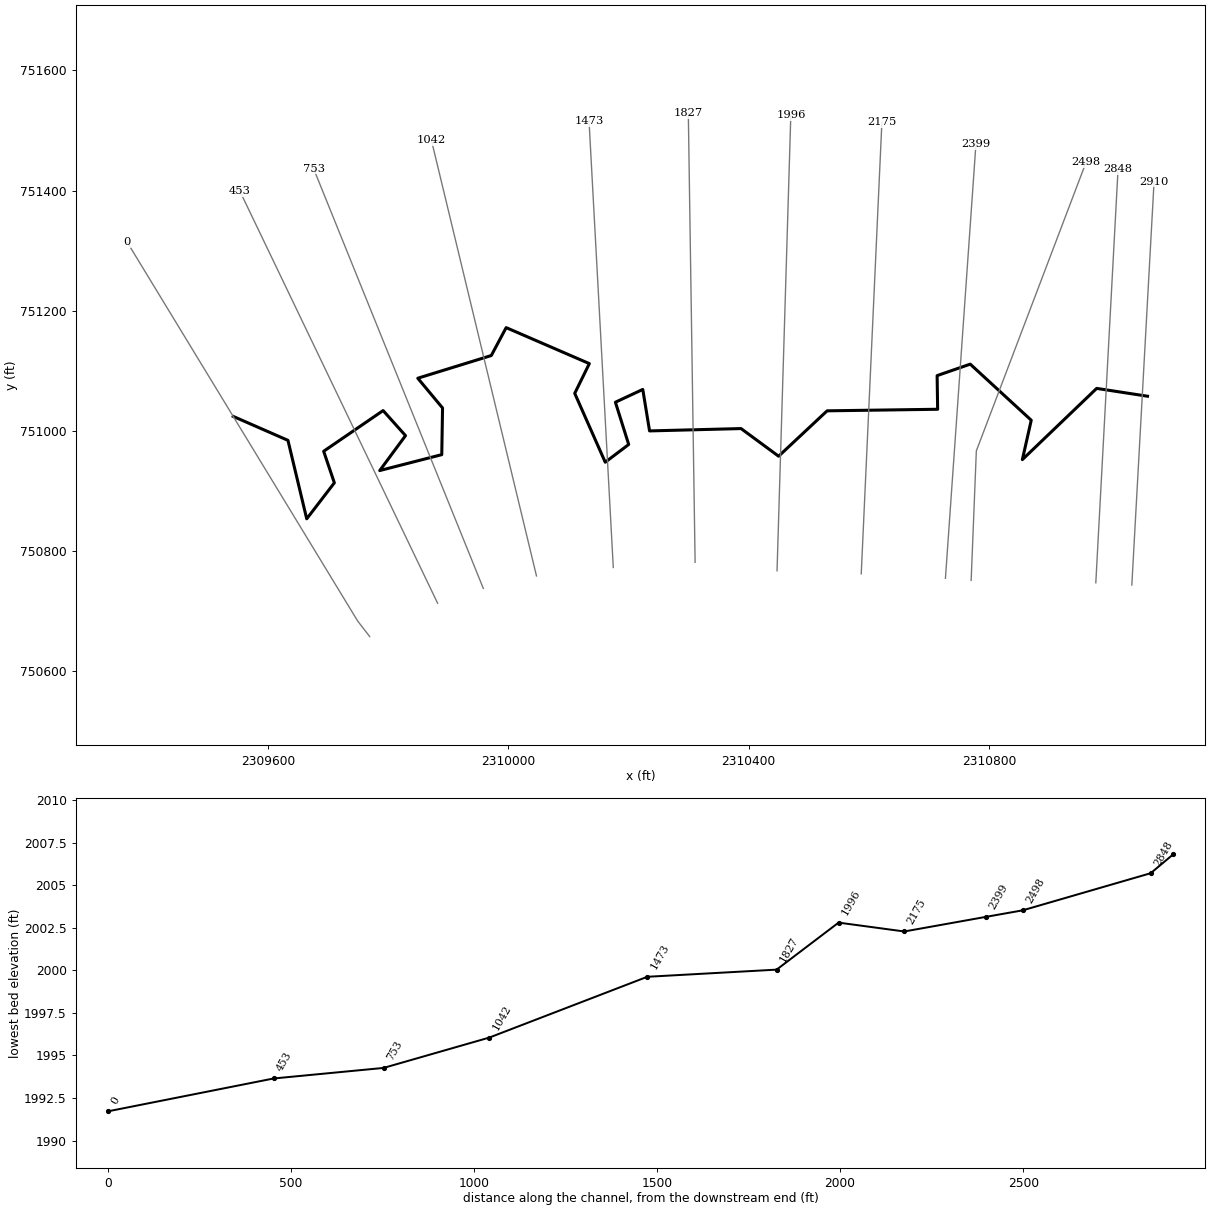
--- BALDLCKFK.prj (project) ---

Proj Title=BALDLCKFK
Current Plan=p01
Default Exp/Contr=0,0
English Units
Geom File=g01
Flow File=f01
Plan File=p01
BEGIN DESCRIPTION:
----------MODEL BY WOOD PLC 2022----------
AFH study
Randolph County, WV
HEC-RAS Version: RAS 6.2
Vertical Datum: NAVD88
Projection: NAD 1983 StatePlane West Virginia S FIPS 4702 (US Feet)
Terrain: 1-meter LIDAR (FEMA Region III 3DEP collected 2016-2018)
Land Use: 2019 NLCD
Hydrologic Method:
WV SIR2010-5033 regression equations
Additional Model Notes:
END DESCRIPTION:
DSS File=dss
DSS Export Rating Curves= 0
DSS Export Rating Curve Sorted= 0
DSS Export Volume Flow Curves= 0
DXF OffsetX= 0
DXF OffsetY= 0
DXF ScaleX= 0
DXF ScaleY= 0

--- BALDLCKFK.p01 (plan) ---

Plan Title=Floodplain
Program Version=6.20
Short Identifier=Floodplain
Geom File=g01
Flow File=f01
Subcritical Flow
K Sum by GR= 0
Std Step Tol= 0.01
Critical Tol= 0.01
Num of Std Step Trials= 20
Max Error Tol= 0.3
Flow Tol Ratio= 0.001
Split Flow NTrial= 30
Split Flow Tol= 0.02
Split Flow Ratio= 0.02
Log Output Level= 0
Friction Slope Method= 1
Unsteady Friction Slope Method= 2
Unsteady Bridges Friction Slope Method= 1
Parabolic Critical Depth
Global Vel Dist= 0 , 0 , 0
Global Log Level= 0
CheckData=True
Encroach Param=-1 ,0,0, 0
Computation Interval=0.1SEC
Output Interval=1SEC
Instantaneous Interval=Max Profile
Mapping Interval=1HOUR
Computation Time Step Use Courant=        0
Computation Time Step Use Time Series=    0
Computation Time Step Count To Double=0
Computation Time Step Max Doubling=0
Computation Time Step Max Halving=0
Computation Time Step Residence Courant=0
Run HTab= 0
Run UNet= 0
Run Sediment= 0
Run PostProcess= 0
Run WQNet= 0
Run RASMapper=-1
UNET Theta= 0
UNET Theta Warmup= 0
UNET ZTol= 0
UNET ZSATol= 0
UNET MxIter= 0
UNET Max Iter WO Improvement= 0
UNET MaxInSteps= 0
UNET DtIC= 0
UNET DtMin= 0
UNET MaxCRTS= 0
UNET WFStab= 0
UNET SFStab= 0
UNET WFX= 1
UNET SFX= 1
UNET Gravity=32.174
UNET 1D Methodology=Finite Difference
UNET DSS MLevel= 1
UNET Pardiso=0
UNET DZMax Abort= 0
UNET Use Existing IB Tables= 0
UNET Froude Reduction=False
UNET Froude Limit= 0
UNET Froude Power= 0
UNET D1 Cores= 0
UNET WindReference=Eulerian
UNET WindDragFormulation=Hsu (1988)
UNET D2 Coriolis=0
UNET D2 Cores= 0
UNET D2 Theta= 1
UNET D2 Theta Warmup= 1
UNET D2 Z Tol= 0.01
UNET D2 Volume Tol= 0.01
UNET D2 Max Iterations= 20
UNET D2 Equation= 0
UNET D2 RampUpFraction=0.1
UNET D2 TimeSlices= 1
UNET D2 Turbulence Formulation=Non-Conservative (original)
UNET D2 Eddy Viscosity=0.3
UNET D2 Transverse Eddy Viscosity=0.1
UNET D2 Smagorinsky Mixing=0
UNET D2 BCVolumeCheck=0
UNET D2 Cores=0
UNET D2 SolverType=PARDISO (Direct)
UNET D2 Minimum Iterations= 2147483647
UNET D2 Maximum Iterations= 2147483647
UNET D2 Restart Number= 10
UNET D2 Relaxation Coeff=1.3
UNET D2 SOR Precondition Iterations= 10
UNET D2 ILUT Maximum Fill= 8
UNET D2 ILUT Tolerance=1E-08
UNET D1D2 MaxIter= 0
UNET D1D2 ZTol=0.01
UNET D1D2 QTol=0.1
UNET D1D2 MinQTol=1
DSS File=dss
Write IC File= 0
Write IC File at Fixed DateTime=0
Write IC File at Sim End=0
Echo Input=False
Echo Parameters=False
Echo Output=False
Write Detailed= 0
HDF Write Warmup=0
HDF Write Time Slices=0
HDF Flush=0
HDF Compression= 1
HDF Chunk Size= 1
HDF Spatial Parts= 1
HDF Use Max Rows=0
HDF Fixed Rows= 1
Calibration Method= 0
Calibration Iterations= 20
Calibration Max Change=0.05
Calibration Tolerance=0.2
Calibration Maximum=1.5
Calibration Minimum=0.5
Calibration Optimization Method= 1
WQ AD Non Conservative
WQ ULTIMATE=-1
WQ Max Comp Step=1HOUR
WQ Output Interval=15MIN
WQ Output Selected Increments= 0
WQ Output face flow=0
WQ Output face velocity=0
WQ Output face area=0
WQ Output face dispersion=0
WQ Output cell volume=0
WQ Output cell surface area=0
WQ Output cell continuity=0
WQ Output cumulative cell continuity=0
WQ Output face conc=0
WQ Output face dconc_dx=0
WQ Output face courant=0
WQ Output face peclet=0
WQ Output face adv mass=0
WQ Output face disp mass=0
WQ Output cell mass=0
WQ Output cell source sink temp=0
WQ Output nsm pathways=0
WQ Output nsm derived pathways=0
WQ Create Restart=0
WQ Fixed Restart=0
WQ System Summary=0
WQ Write To DSS=0
Sorting and Armoring Iterations= 10
XS Update Threshold= 0.02
Bed Roughness Predictor= 0
Hydraulics Update Threshold= 0.02
Energy Slope Method= 1
Volume Change Method= 1
Sediment Retention Method= 0
Sediment TS Multiplier= 1
Warm Up Method= 0
XS Weighting Method= 0
Number of US Weighted Cross Sections= 1
Number of DS Weighted Cross Sections= 1
Upstream XS Weight=0
Main XS Weight=1
Downstream XS Weight=0
Number of DS XS's Weighted with US Boundary= 1
Upstream Boundary Weight= 1
Weight of XSs Associated with US Boundary= 0
Number of US XS's Weighted with DS Boundary= 1
Downstream Boundary Weight= 0.5
Weight of XSs Associated with DS Boundary= 0.5
Percentile Method= 0
Sediment Output Level= 3
Mass or Volume Output= 0
Output Increment Type= 1
Profile and TS Output Increment= 1
Transport Output Increment 1
XS Output Flag= 0
XS Output Increment= 10
Read HDF5 Sediment Hotstart= 0
Sediment Hotstart Type= 0
Write Gradation File= 0
Read Gradation Hotstart= 0
Write HDF5 File= 1
Write Binary Output= 1
Write DSS Sediment File= 0
DSS Sediment Output Type= 1
SV Curve= 0
Specific Gage Flag= 0
Subcell Erosion Methods= 0
Subcell Deposition Methods= 0
Advection Scheme= 1
Matrix Solver= 0
Implicit Weighting Factor= 1
Maximum Outer Loop Convergence Iterations= 5
Convergence Maximum Absolute= 0.001
Convergence RMSE= 0.0001
Grain Fractions Max Abs Error= 0.001
Max Subgrid Regions= 1
Max Subgrid Length Scale= 3.402823E+38
Initial Layer Thickness= 3.402823E+38
Min Layer Thickness= 3.402823E+38
Max Layer Thickness= 3.402823E+38
Number of Layers= 5

--- BALDLCKFK.f01 (steady flow) ---

Flow Title=Flow
Program Version=6.20
Number of Profiles= 1
Profile Names=P100yr
River Rch & RM=BALDLCKFK,Main,2910
     397
Boundary for River Rch & Prof#=BALDLCKFK,Main            , 1
Up Type= 0
Dn Type= 3
Dn Slope=0.00597
DSS Import GetInterval= 0
DSS Import GetPeak= 0
DSS Import FillOption= 0

--- BALDLCKFK.g01 (geometry) ---

Geom Title=Geometry
Program Version=6.20

River Reach=BALDLCKFK       ,Main
Reach XY= 30
     2311063.916       751057.86      2310979.28      751070.881
     2310855.582      750952.392     2310870.339       751017.93
     2310768.777      751111.246     2310713.655      751092.148
     2310714.523      751036.159     2310530.495      751033.555
     2310449.766      750958.034     2310387.266      751004.041
     2310234.922      751000.135     2310223.638      751069.145
     2310178.065      751047.878       2310200.2      750977.565
     2310161.138      750948.051     2310110.357      751062.634
     2310134.662      751112.114     2309996.207       751172.01
     2309971.468      751125.569     2309849.072      751087.808
     2309890.304      751038.329     2309889.003      750960.638
     2309785.704      750934.162     2309828.673      750992.322
     2309791.346      751033.989     2309692.388       750966.28
     2309710.183      750913.763     2309664.176      750853.867
     2309632.926      750984.423 2309541.7525898751024.317299778

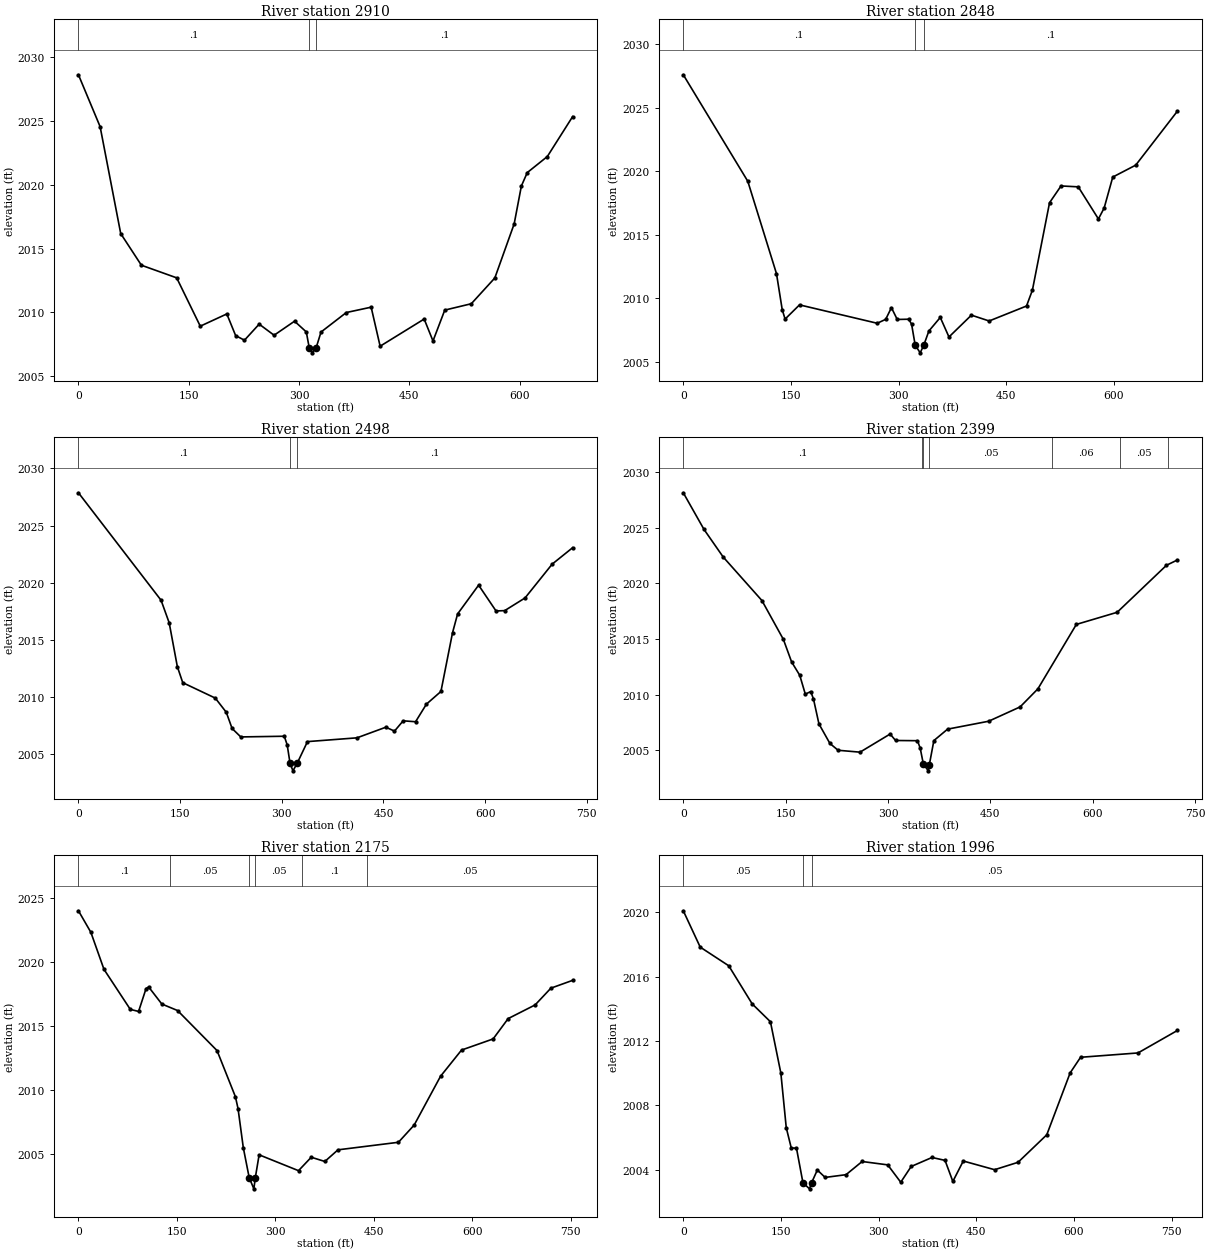
Type RM Length L Ch R = 1 ,2910    ,62.2,62.2,62.2
XS GIS Cut Line= 2
2311037.81237332 750743.732149062311074.83112155751414.846229765
#Sta/Elev= 30
       0 2028.62    29.5 2024.55    57.5 2016.17    85.6 2013.69   133.6  2012.7
   165.7 2008.91   201.8 2009.87   213.8 2008.17   225.8 2007.81   245.8 2009.07
   266.1  2008.2   293.9  2009.3   309.9 2008.46   313.9 2007.21   317.9 2006.82
   323.32007.219   329.9 2008.45   364.3 2009.98   398.1  2010.4   410.3 2007.34
   470.2 2009.47   482.2 2007.75   498.2 2010.17   534.3 2010.67   566.3 2012.69
   592.6 2016.93   602.4  2019.9   610.4 2020.95   637.7 2022.21   672.1 2025.34
#Mann= 3 ,-1,0
       0      .1       0   313.9    .045       0   323.3      .1       0
Bank Sta=313.9,323.3
XS Rating Curve= 0 ,0
Exp/Cntr(USF)=0,0
Exp/Cntr=0.3,0.1

Type RM Length L Ch R = 1 ,2848    ,349.7,349.7,349.7
XS GIS Cut Line= 2
2310977.84026172 750747.450949022311014.85900994751435.283174084
#Sta/Elev= 30
       0 2027.61    89.9 2019.22   129.9 2011.94   137.9  2009.1   141.9 2008.36
     162 2009.48   270.3 2008.03   282.1 2008.34   290.1 2009.26   298.2 2008.33
   314.2 2008.35   318.2 2007.96   323.2 2006.31   330.2  2005.7  335.142006.295
   342.3 2007.42   358.2 2008.49   370.3 2006.95   401.6 2008.67   426.3 2008.21
   478.4 2009.39   486.6 2010.64   510.5 2017.53   526.5 2018.85   550.5 2018.78
   578.6 2016.25   586.6 2017.11   598.6 2019.55   630.6 2020.49   688.8 2024.75
#Mann= 3 ,-1,0
       0      .1       0   323.2    .045       0  335.14      .1       0
Bank Sta=323.2,335.14
XS Rating Curve= 0 ,0
Exp/Cntr(USF)=0,0
Exp/Cntr=0.3,0.1

Type RM Length L Ch R = 1 ,2498    ,99.6,99.6,99.6
XS GIS Cut Line= 3
2310770.32206358750751.4177466992310778.94558893750966.902451118
 2310961.4982278751446.832139866
#Sta/Elev= 30
       0 2027.87   121.9 2018.46   133.9 2016.48   145.9 2012.65   153.9 2011.24
   201.9 2009.89   218.1 2008.65   226.7 2007.23   239.5 2006.49   303.7 2006.55
     308 2005.79   312.2 2004.18   316.5 2003.52  322.892004.204   337.9 2006.08
   410.9 2006.41   453.5 2007.34   466.3    2007   479.1  2007.9   497.4 2007.82
   513.4 2009.36   534.8 2010.47   551.9 2015.61   559.4 2017.26   590.4 2019.78
   616.1 2017.52   628.9 2017.55   658.9 2018.66   698.9 2021.62   729.1 2023.06
#Mann= 3 ,-1,0
       0      .1       0   312.2    .045       0  322.89      .1       0
Bank Sta=312.2,322.89
XS Rating Curve= 0 ,0
Exp/Cntr(USF)=0,0
Exp/Cntr=0.3,0.1

Type RM Length L Ch R = 1 ,2399    ,223.5,223.5,223.5
XS GIS Cut Line= 2
2310727.49563265750754.8555598422310778.27580854751477.244513634
#Sta/Elev= 30
       0 2028.15    30.4 2024.85    58.5 2022.37   115.2 2018.46   146.7 2014.96
   158.7 2012.94   170.7 2011.73   178.8 2010.04   186.8 2010.27   190.8  2009.6
   198.8 2007.36   214.9  2005.6   226.9 2004.99     259 2004.82   303.1 2006.45
   311.1 2005.87   343.2 2005.85   347.2 2005.18   351.9 2003.72   359.2 2003.14
   360.6  2003.7   367.2 2005.86   387.3 2006.89   447.4  2007.6   493.6 2008.89
   519.6 2010.51     576 2016.31   635.8  2017.4   708.1 2021.63   724.2 2022.11
#Mann= 7 ,-1,0
       0      .1       0     350     .05       0   351.9    .045       0
   360.6     .05       0     540     .06       0     640     .05       0
     710      .1       0
Bank Sta=351.9,360.6
XS Rating Curve= 0 ,0
Exp/Cntr(USF)=0,0
Exp/Cntr=0.3,0.1

Type RM Length L Ch R = 1 ,2175    ,179.5,179.5,179.5
XS GIS Cut Line= 2
2310587.32996651750762.293159762 2310621.7294405751514.167376975
#Sta/Elev= 30
       0 2024.02    18.9 2022.34    38.9 2019.44      79 2016.31    91.6 2016.15
     103 2017.94     107 2018.06     127 2016.73     151 2016.22   211.1 2013.09
   239.1 2009.48   243.1 2008.55   251.1  2005.5   260.1 2003.15   267.2 2002.28
  269.352003.135   275.2 2004.94   335.2  2003.7   354.6 2004.75   375.3 2004.42
   395.3 2005.33   487.4 2005.92   511.4 2007.27   551.5 2011.08   583.5 2013.13
   631.6    2014   654.5 2015.59   695.6 2016.66   719.6 2017.97   752.7 2018.58
#Mann= 6 ,-1,0
       0      .1       0     140     .05       0   260.1    .045       0
  269.35     .05       0     340      .1       0     440     .05       0
Bank Sta=260.1,269.35
XS Rating Curve= 0 ,0
Exp/Cntr(USF)=0,0
Exp/Cntr=0.3,0.1

Type RM Length L Ch R = 1 ,1996    ,169.2,169.2,169.2
XS GIS Cut Line= 2
2310447.16430037750767.4287001212310470.09728303751525.855198094
#Sta/Elev= 30
       0 2020.09      26 2017.83    69.8 2016.67   105.8  2014.3   133.8 2013.19
   149.8    2010   158.1  2006.6   165.8 2005.34   173.8 2005.33  183.732003.177
   193.8  2002.8   196.9 2003.17   205.8 2003.97   217.8 2003.51   249.9 2003.68
   274.6  2004.5   313.9 2004.29   333.9 2003.21   349.9 2004.19   381.9 2004.75
   401.9 2004.57   413.9 2003.26   429.9 2004.53     478 2003.99     514 2004.45
   558.1 2006.16     594 2010.01     610 2010.98   698.2 2011.25   758.8 2012.65
#Mann= 3 ,-1,0
       0     .05       0  183.73    .045       0   196.9     .05       0
Bank Sta=183.73,196.9
XS Rating Curve= 0 ,0
Exp/Cntr(USF)=0,0
Exp/Cntr=0.3,0.1

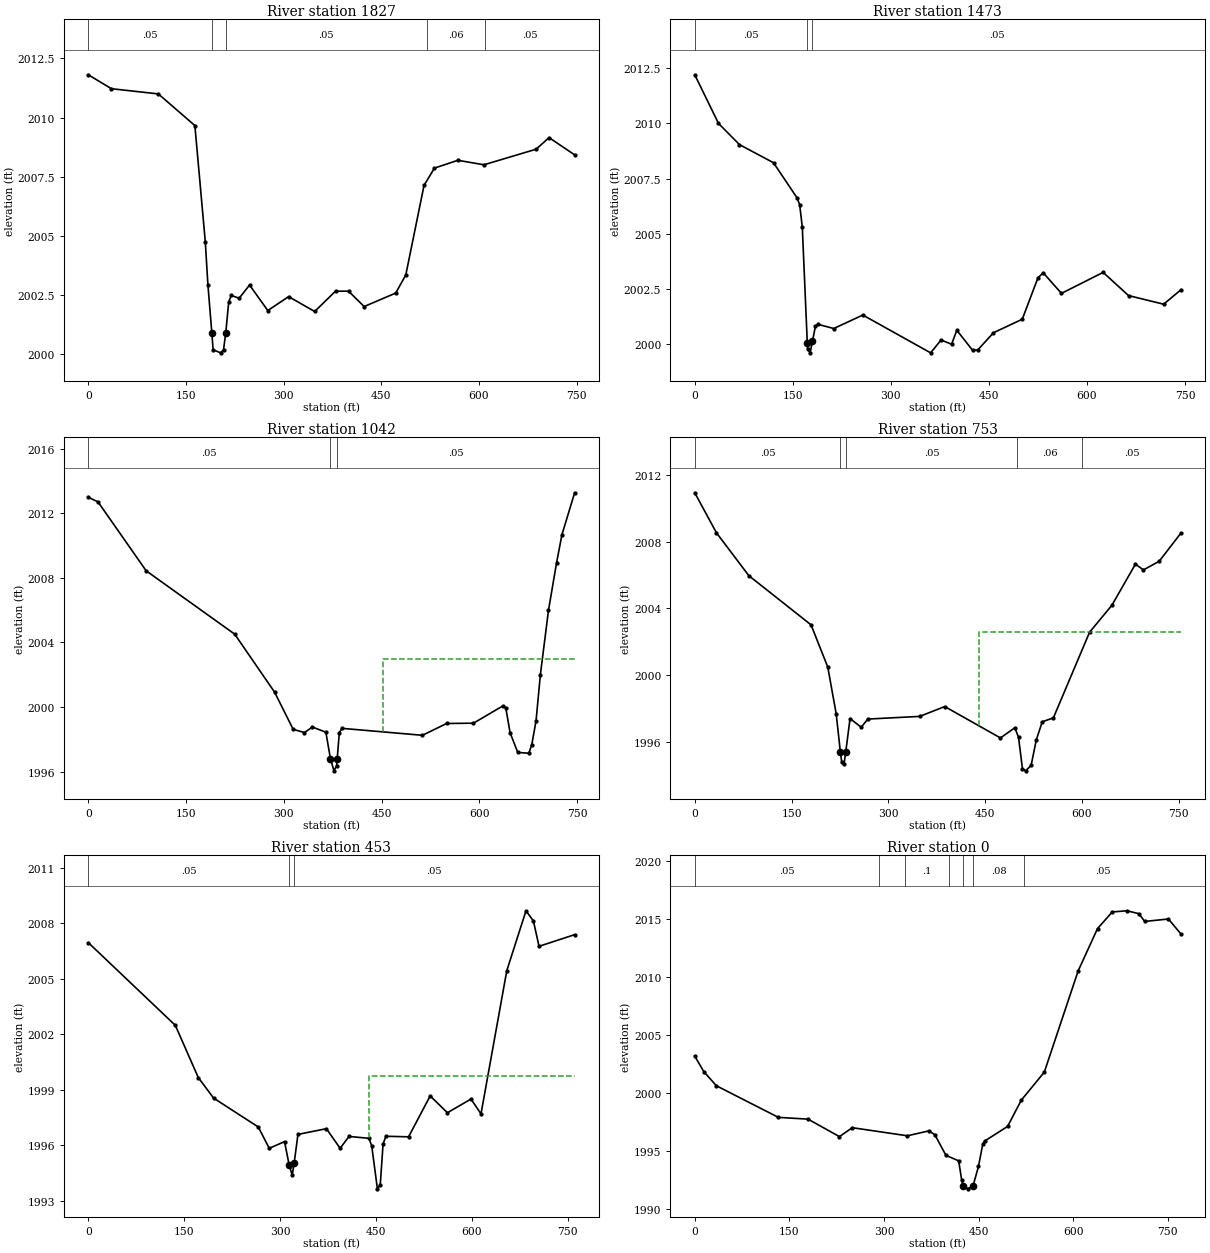
Type RM Length L Ch R = 1 ,1827    ,353.2,353.2,353.2
XS GIS Cut Line= 2
2310310.76181502 750781.544057062310299.45913071751528.418587628
#Sta/Elev= 30
       0 2011.81    35.6 2011.22   107.6    2011   163.7 2009.66   179.7 2004.74
   183.7 2002.93  189.722000.896   191.7 2000.17   203.2 2000.04   207.7 2000.17
   211.1 2000.87   215.7  2002.2   219.7 2002.47   231.7 2002.35   247.7 2002.91
   275.7 2001.83   307.7 2002.42   347.7 2001.79   379.7 2002.65   399.7 2002.65
   423.7    2002   472.2 2002.57   487.7 2003.34   515.7 2007.13   531.7 2007.86
   567.7 2008.19   607.7    2008   687.9 2008.66   707.7 2009.15     747 2008.42
#Mann= 5 ,-1,0
       0     .05       0  189.72    .045       0   211.1     .05       0
     520     .06       0     610     .05       0
Bank Sta=189.72,211.1
XS Rating Curve= 0 ,0
Exp/Cntr(USF)=0,0
Exp/Cntr=0.3,0.1

Type RM Length L Ch R = 1 ,1473    ,431.7,431.7,431.7
XS GIS Cut Line= 2
2310174.54142441750772.8910377542310134.17346789751515.792305224
#Sta/Elev= 30
       0  2012.2    36.3    2010    68.4 2009.04   120.5 2008.22   156.5 2006.63
   160.5 2006.32   164.5 2005.31  172.142000.084   172.5 1999.81   176.5 1999.62
     180 2000.14   184.6 2000.82   188.6 2000.91   212.6 2000.72   257.1 2001.33
   360.8 1999.62   376.8  2000.2   392.9 2000.01   400.9 2000.64   424.9 1999.74
   432.9 1999.75     457 2000.53     501 2001.14   525.1 2003.02   533.1 2003.24
     561 2002.31   624.7 2003.26   663.6 2002.21   717.3 2001.82     744 2002.48
#Mann= 3 ,-1,0
       0     .05       0  172.14    .045       0     180     .05       0
Bank Sta=172.14,180
XS Rating Curve= 0 ,0
Exp/Cntr(USF)=0,0
Exp/Cntr=0.3,0.1

Type RM Length L Ch R = 1 ,1042    ,288.6,288.6,288.6
XS GIS Cut Line= 2
2310046.68556988750758.8357423852309871.68395874751484.164408617
#Sta/Elev= 30
       0 2012.98    14.8  2012.7    88.8 2008.43   224.6 2004.51   285.8 2000.92
   314.3 1998.62   331.6 1998.42   343.9 1998.76   364.5 1998.44  371.431996.808
   376.9 1996.05     381 1996.38   381.9 1996.81   385.1 1998.41   389.2 1998.68
   512.6 1998.25   549.7 1998.98   590.9    1999   636.1 2000.07   640.5 1999.94
   647.1 1998.41   658.8 1997.19   675.8 1997.14   680.3 1997.66   686.9 1999.14
   693.5 2001.99     706 2005.99   718.4 2008.93   726.6 2010.66   746.1 2013.26
#Mann= 3 ,-1,0
       0     .05       0  371.43    .045       0   381.9     .05       0
#XS Ineff= 2 , 0
                          452.55            2003
Permanent Ineff=
       F       F
Bank Sta=371.43,381.9
XS Rating Curve= 0 ,0
Exp/Cntr(USF)=0,0
Exp/Cntr=0.3,0.1

Type RM Length L Ch R = 1 ,753     ,300.3,300.3,300.3
XS GIS Cut Line= 2
2309958.14166157750738.1046020722309675.58943441751436.602850336
#Sta/Elev= 30
       0 2010.92    33.5 2008.53    83.7 2005.96   180.2 2003.01   206.1 2000.48
   219.1 1997.69  225.551995.422   227.7 1994.78   231.2 1994.66   233.9  1995.4
   240.6  1997.4   257.9 1996.88   268.1 1997.37   348.5 1997.53   387.3 1998.12
   473.6 1996.24   495.9 1996.85   501.6 1996.28   507.7  1994.4   512.5 1994.27
   521.1 1994.59   529.2 1996.13   538.4 1997.21   555.6 1997.44   611.7 2002.57
   646.2 2004.18   682.8 2006.65   695.1  2006.3   719.6 2006.82   753.5 2008.52
#Mann= 5 ,-1,0
       0     .05       0  225.55    .045       0   233.9     .05       0
     500     .06       0     600     .05       0
#XS Ineff= 2 , 0
                          439.69         2002.58
Permanent Ineff=
       F       F
Bank Sta=225.55,233.9
XS Rating Curve= 0 ,0
Exp/Cntr(USF)=0,0
Exp/Cntr=0.3,0.1

Type RM Length L Ch R = 1 ,453     ,452.8,452.8,452.8
XS GIS Cut Line= 2
2309882.08720842750713.4141749882309552.77855099751399.374276192
#Sta/Elev= 30
       0 2006.95   136.2 2002.48   172.1 1999.66   196.1 1998.55     266 1996.99
   283.1 1995.84     307  1996.2  314.231994.947     319 1994.39     322 1995.02
     328 1996.59   372.5  1996.9     394 1995.84   407.9 1996.48     439 1996.38
   443.4 1995.98   452.3 1993.65   456.8 1993.87   461.2 1996.07   465.6 1996.49
   501.1 1996.46   534.9 1998.67   561.9 1997.76   598.7  1998.5   614.4  1997.7
   654.8 2005.44   684.8 2008.67   696.4 2008.12   705.2 2006.75   760.9 2007.38
#Mann= 3 ,-1,0
       0     .05       0  314.23    .045       0     322     .05       0
#XS Ineff= 2 , 0
                          438.99         1999.76
Permanent Ineff=
       F       F
Bank Sta=314.23,322
XS Rating Curve= 0 ,0
Exp/Cntr(USF)=0,0
Exp/Cntr=0.3,0.1

Type RM Length L Ch R = 1 ,0       ,314.9,314.9,314.9
BEGIN DESCRIPTION:
Shared XS
END DESCRIPTION:
XS GIS Cut Line= 3
2309769.01319984750657.9447495552309749.03228184 750683.77115292
2309365.21304987751314.359510368
#Sta/Elev= 30
       0 2003.18    14.2 2001.85    34.3 2000.62   132.6 1997.89   179.5 1997.74
   229.3 1996.23   249.7    1997     337  1996.3   371.5 1996.73   380.7 1996.38
   398.2 1994.61   418.3 1994.14     423 1992.52  425.78 1991.99   433.1 1991.72
   441.1 1991.97   449.7 1993.65   456.4 1995.55   459.3 1995.84   495.9 1997.11
   517.5 1999.37   554.1  2001.8   607.8 2010.55   638.4 2014.19   661.8 2015.63
   685.2 2015.73   703.8 2015.48   713.3 2014.81   750.8 2015.02   770.9 2013.71
#Mann= 7 ,-1,0
       0     .05       0  292.65     .08       0  332.65      .1       0
  402.65     .08       0  425.78    .045       0   441.1     .08       0
  522.65     .05       0
Bank Sta=425.78,441.1
XS Rating Curve= 0 ,0
Exp/Cntr=0.3,0.1
LCMann Table=0

Chan Stop Cuts=-1
Use User Specified Reach Order=0
Composite Channel Slope=5